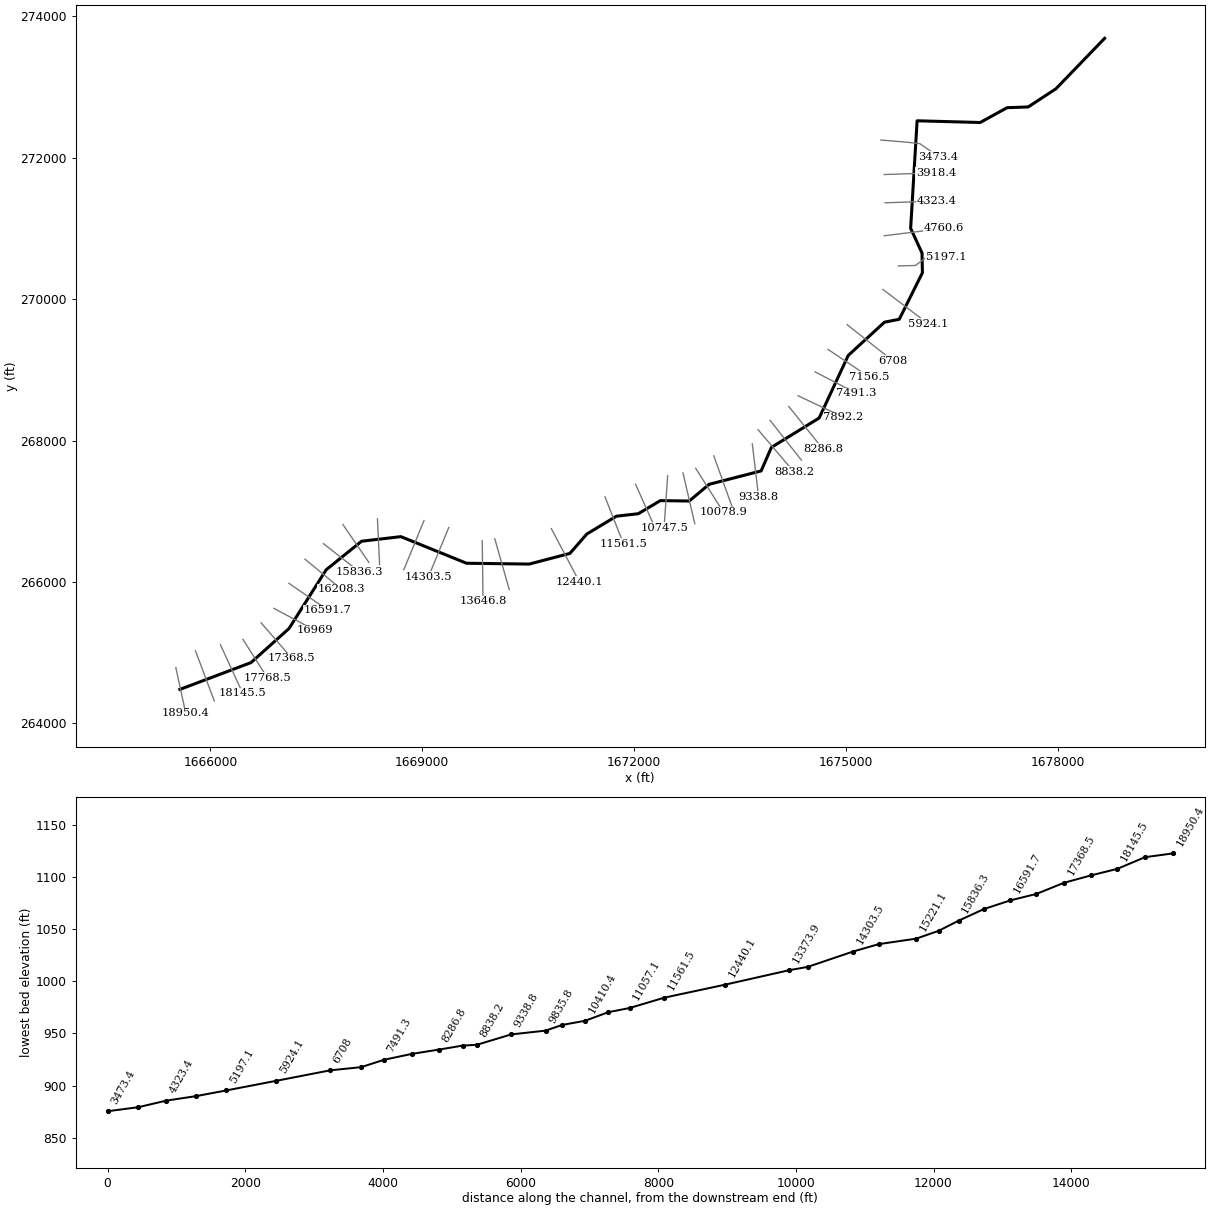
--- COWCRK.prj (project) ---

Proj Title=COWCRK
Current Plan=p01
Default Exp/Contr=0,0
English Units
Geom File=g01
Flow File=f01
Plan File=p01
BEGIN DESCRIPTION:
END DESCRIPTION:
DSS Export Rating Curves= 0
DSS Export Rating Curve Sorted= 0
DSS Export Volume Flow Curves= 0
DXF OffsetX= 0
DXF OffsetY= 0
DXF ScaleX= 0
DXF ScaleY= 0

--- COWCRK.p01 (plan) ---

Plan Title=Floodplain
Program Version=4.00
Geom File=g01
Flow File=f01
K Sum by GR=0
Std Step Tol=0.01
Critical Tol=0.01
Num of Std Step Trials=20
Max Error Tol=0.3
Flow Tol Ratio=0.001
Split Flow NTrial=30
Split Flow Tol=0.02
Split Flow Ratio=0.02
Log Output Level=0
Friction Slope Method=1
Unsteady Friction Slope Method=2
Unsteady Bridges Friction Slope Method=1
Global Log Level=0
CheckData=False
Run HTab=0
Run UNet=0
Run PostProcess=0
UNET Theta=0
UNET Theta Warmup=0
UNET ZTol=0
UNET ZSATol=0
UNET MxIter=0
UNET MaxInSteps=0
UNET DtIC=0
UNET DtMin=0
UNET MaxCRTS=0
UNET WFStab=0
UNET SFStab=0
UNET WFX=0
UNET SFX=0
UNET DSS MLevel=0
UNET DZMax Abort=0
UNET Convert EG Bridges=0
UNET Use Existing IB Tables=0
UNET Froude Limit=0
UNET Froude Power=0
Write IC File=0
Echo Input=False
Echo Output=False
Write Detailed=0

--- COWCRK.f01 (steady flow) ---

Flow Title=NFF Regression Equation
Program Version=4.00
Number of Profiles=1
Profile Names=P100yr
River Rch & RM=COWCRK,Main      ,18950.4
947.6503
River Rch & RM=COWCRK,Main      ,15547
1004.888
River Rch & RM=COWCRK,Main      ,15221.1
1144.245
River Rch & RM=COWCRK,Main      ,13646.8
1623.489
River Rch & RM=COWCRK,Main      ,13646.8
1175.838
River Rch & RM=COWCRK,Main      ,10747.5
1724.907
River Rch & RM=COWCRK,Main      ,8838.2
1896.848
River Rch & RM=COWCRK,Main      ,6708
1948.397
River Rch & RM=COWCRK,Main      ,2646.7
2162.046
River Rch & RM=COWCRK,Main      ,1902
2169.832
Boundary for River Rch & Prof#=COWCRK,Main      ,1
Up Type=0
Dn Type=3
Dn Slope=0.0095

--- COWCRK.g01 (geometry) ---

Geom Title=USGS 10m DEM
Program Version=4.10

River Reach=COWCRK          ,Main
Reach XY= 30
     1665568.667      264480.723     1666576.304      264860.613
      1667113.71      265342.426     1667639.534      266172.858
     1668141.036       266577.07     1668696.974       266641.93
     1669627.011      266265.514     1670514.194      266253.932
     1671089.821      266404.498     1671329.569      266678.992
     1671748.188      266931.018     1672058.079      266966.227
     1672370.794      267151.539      1672779.64      267145.748
     1673061.083      267382.022       1673797.7      267571.967
     1673942.476      267904.371     1674618.866      268320.166
     1675030.028      269205.033     1675543.112      269675.264
     1675752.747      269716.959     1676080.519      270374.818
     1676074.727      270653.946     1675913.737      271003.723
     1676005.235      272524.443      1676898.21      272500.121
     1677279.259      272709.756     1677578.075       272720.18
     1677970.706      272977.301     1678659.837      273690.754

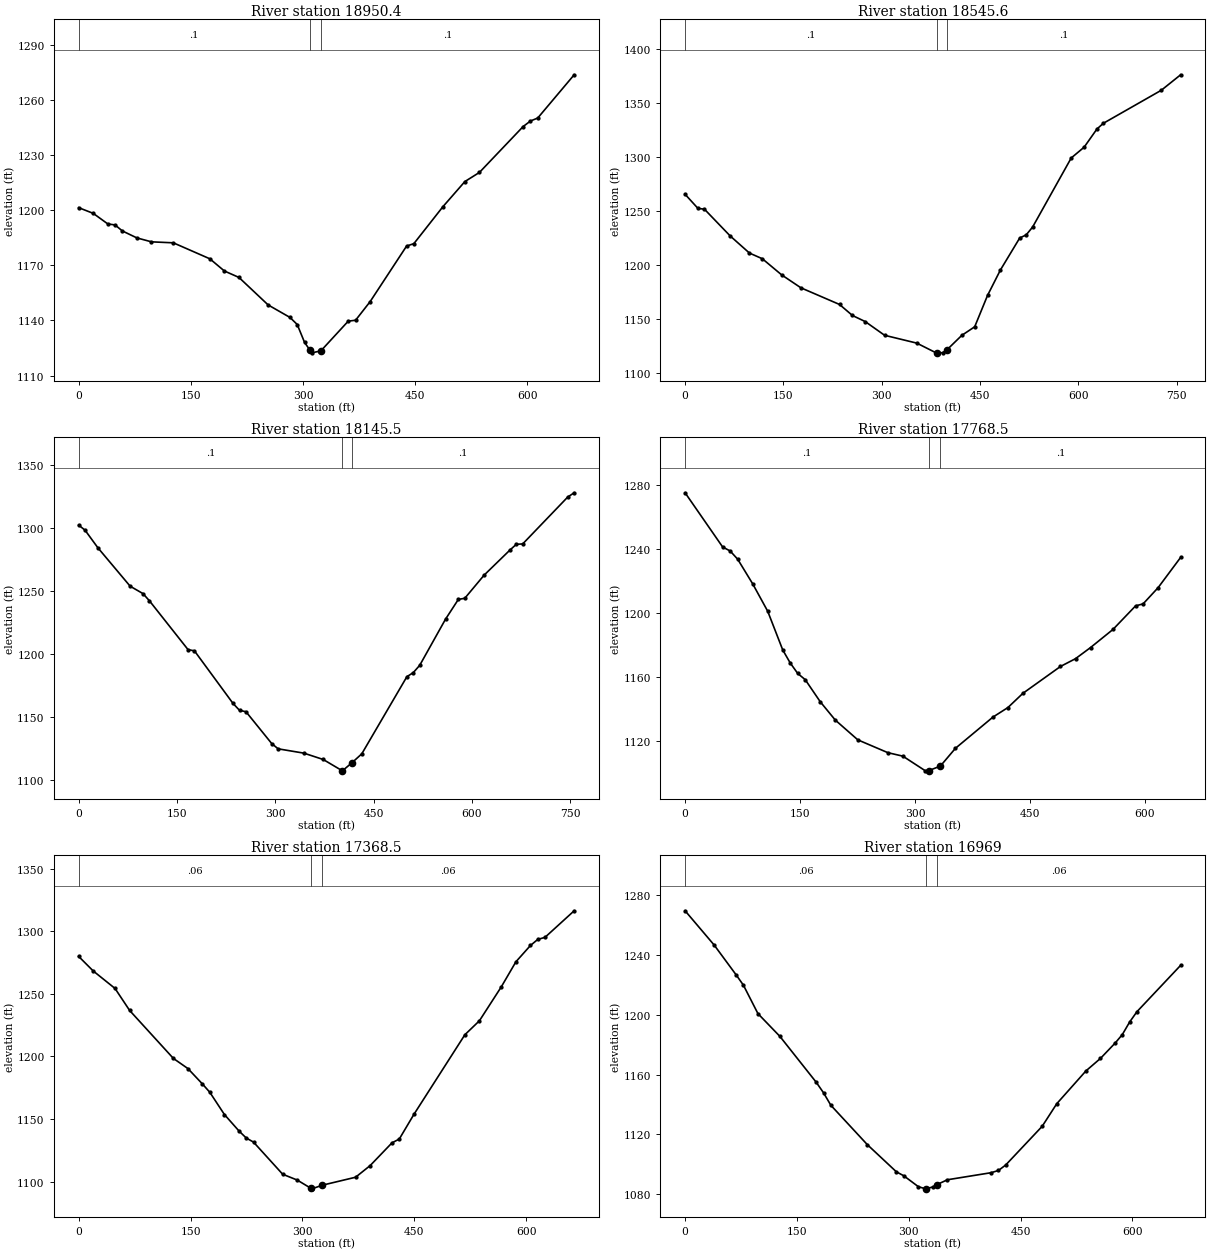
Type RM Length L Ch R = 1 ,18950.4 ,401.3,404.8,408.2
XS GIS Cut Line= 2
     1665511.462      264789.226     1665652.181      264141.906
#Sta/Elev= 30
       0  1201.4    19.5  1198.3      39 1192.54    48.7 1191.99    58.4 1188.74
    77.9 1184.93    97.4  1182.8   126.6 1182.26   175.4 1173.57   194.8 1166.94
   214.3 1163.43   253.3 1148.47   282.5 1141.67   292.2 1137.82     302 1128.08
   308.8  1124.1   311.7  1122.4   323.8 1123.47   360.4 1139.64   370.2 1140.14
   389.7 1150.29   438.4 1180.51   448.1 1181.81   487.1    1202   516.3  1215.6
   535.8 1220.58   594.2 1245.54     604 1248.55   613.7 1250.17   662.4  1273.7
#Mann= 3 , 0 , 0
       0      .1       0   308.8    .045       0   323.8      .1       0
Bank Sta=308.8,323.8
XS Rating Curve= 0 ,0
Exp/Cntr=0.3,0.1

Type RM Length L Ch R = 1 ,18545.6 ,398.2,400.1,401.7
XS GIS Cut Line= 2
     1665789.623      265026.588     1666055.251      264318.481
#Sta/Elev= 30
       0 1265.68    19.6 1252.61    29.5 1251.88    68.8 1227.08    98.2 1211.22
   117.9 1205.94   147.3 1191.03   176.8    1179   235.7 1163.58   255.4 1153.37
     275  1147.7   304.5 1135.02   353.6 1127.77   383.1 1118.76   384.3 1118.77
   392.9 1118.87   399.3 1121.36   422.3 1134.95     442 1142.92   461.6 1171.98
   481.3  1195.6   510.7 1225.19   520.6 1228.07   530.4 1235.34   589.3 1299.32
     609 1309.32   628.6  1326.2   638.4 1331.48   726.8 1362.08   756.3 1376.42
#Mann= 3 , 0 , 0
       0      .1       0   384.3    .045       0   399.3      .1       0
Bank Sta=384.3,399.3
XS Rating Curve= 0 ,0
Exp/Cntr=0.3,0.1

Type RM Length L Ch R = 1 ,18145.5 ,374.1,377,379.7
XS GIS Cut Line= 2
     1666142.709      265112.264     1666458.952      264425.526
#Sta/Elev= 30
       0 1302.12     9.8 1298.07    29.5 1284.06    78.6 1253.74    98.2 1247.88
     108  1242.2   166.9 1203.56   176.7 1202.58   235.6 1160.93   245.5  1155.5
   255.3 1154.42   294.6  1129.2   304.4 1125.04   343.7 1121.63   373.1 1116.62
   402.4 1107.63   417.4 1114.22     432  1121.1   500.8 1182.15   510.6 1185.38
   520.4 1191.17   559.7 1227.62   579.3  1243.3   589.1 1244.18   618.6 1262.49
   657.9  1282.3   667.7 1286.89   677.5 1287.22   746.2 1324.32     756 1327.68
#Mann= 3 , 0 , 0
       0      .1       0   402.4    .045       0   417.4      .1       0
Bank Sta=402.4,417.4
XS Rating Curve= 0 ,0
Exp/Cntr=0.3,0.1

Type RM Length L Ch R = 1 ,17768.5 ,396.4,400,403.2
XS GIS Cut Line= 2
     1666460.728      265189.522     1666808.176      264644.076
#Sta/Elev= 30
       0 1274.96      49 1241.13    58.8 1238.64    68.6 1233.52    88.2 1218.15
   107.8 1201.05   127.4 1176.91   137.2 1168.75     147  1162.2   156.8 1158.32
   176.4 1144.54     196 1133.12   225.4 1120.78   264.6 1112.78   284.2  1110.6
   313.6 1101.44   318.1 1101.61   333.1 1104.39   352.8  1115.5   401.7 1134.96
   421.3 1140.94   440.9 1149.83   489.9 1166.58   509.5 1171.43   529.1 1178.37
   558.5 1189.72   587.9 1204.39   597.7 1205.62   617.3 1215.75   646.7 1234.63
#Mann= 3 , 0 , 0
       0      .1       0   318.1    .045       0   333.1      .1       0
Bank Sta=318.1,333.1
XS Rating Curve= 0 ,0
Exp/Cntr=0.3,0.1

Type RM Length L Ch R = 1 ,17368.5 ,391.2,399.6,407.8
XS GIS Cut Line= 2
     1666718.534      265422.886     1667153.529      264920.947
#Sta/Elev= 30
       0 1279.86    19.5 1268.24    48.8 1254.25    68.4 1236.65     127 1198.38
   146.5 1190.27     166 1177.94   175.8 1171.36   195.4 1153.59   214.9 1140.47
   224.7 1134.81   234.4 1131.57   273.5  1105.9     293 1101.25   311.7 1094.55
   312.6 1094.24   326.7 1097.16   371.2  1103.5   390.7 1112.78     420 1130.96
   429.8 1134.02   449.3 1153.61   517.7 1217.28   537.2 1228.45   566.5 1255.52
   586.1 1275.55   605.6 1288.57   615.4  1293.4   625.1 1295.07   664.2 1316.28
#Mann= 3 , 0 , 0
       0     .06       0   311.7    .045       0   326.7     .06       0
Bank Sta=311.7,326.7
XS Rating Curve= 0 ,0
Exp/Cntr=0.3,0.1

Type RM Length L Ch R = 1 ,16969   ,379.6,377.2,374.6
XS GIS Cut Line= 2
     1666898.619      265627.913     1667485.093      265315.222
#Sta/Elev= 30
       0 1269.57    39.1 1246.58    68.4 1226.75    78.2 1219.82    97.7 1200.78
   127.1 1185.58   175.9 1154.85   185.7  1147.8   195.5 1139.47   244.4 1113.15
   283.4 1094.96   293.2 1092.35   312.8 1085.05   322.5 1083.59   322.8 1083.63
   332.3 1084.84   337.8 1086.45   351.9 1089.67   410.5 1094.39   420.3 1095.89
     430 1099.54   478.9 1125.41   498.5 1140.55   537.6 1162.47   557.1 1170.84
   576.7 1181.06   586.4 1186.77   596.2 1195.16     606 1202.08   664.6 1233.08
#Mann= 3 , 0 , 0
       0     .06       0   322.8    .045       0   337.8     .06       0
Bank Sta=322.8,337.8
XS Rating Curve= 0 ,0
Exp/Cntr=0.3,0.1

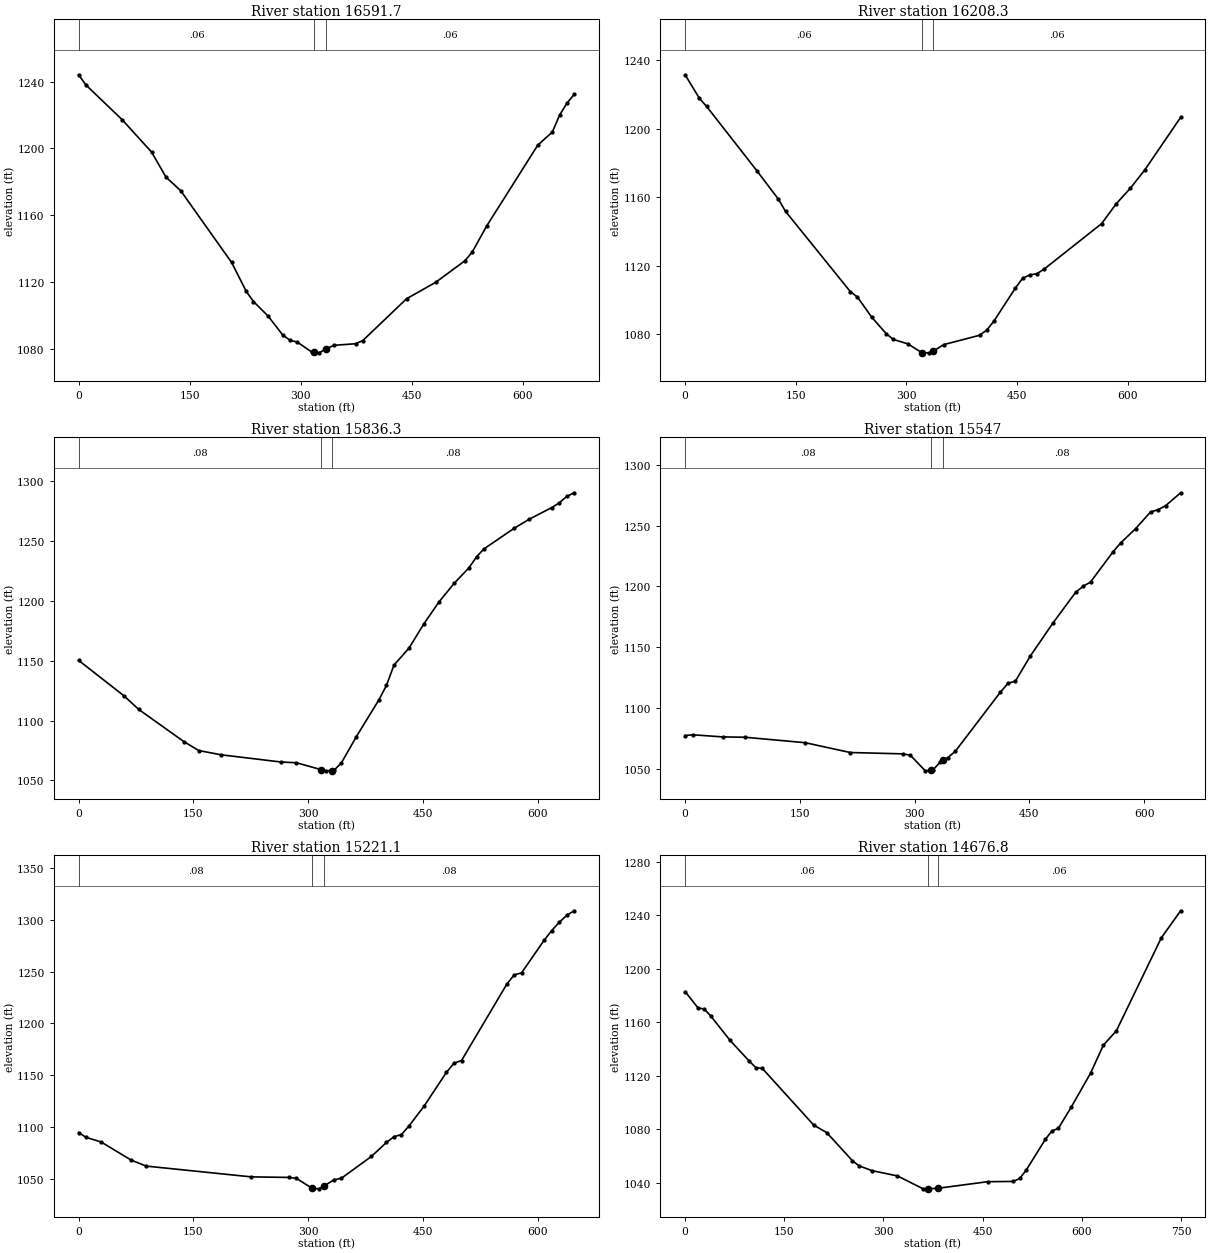
Type RM Length L Ch R = 1 ,16591.7 ,385.3,383.4,381.4
XS GIS Cut Line= 2
     1667112.881      265981.343     1667664.237      265602.318
#Sta/Elev= 30
       0 1244.09     9.8    1238      59 1217.06    98.4  1197.8   118.1 1182.68
   137.8 1174.63   206.6 1131.57   226.3 1114.28   236.1 1108.15   255.8 1099.48
   275.5 1088.14   285.3 1084.98   295.2 1083.87   314.9 1077.87   318.4 1077.71
   324.7 1077.42   333.4 1079.59   344.4  1081.9   373.9 1082.88   383.7 1084.78
   442.8 1109.85   482.1 1119.68   521.5 1132.59   531.3 1137.71     551 1153.48
   619.9  1201.9   639.6 1209.76   649.4 1219.89   659.2 1226.98   669.1 1232.32
#Mann= 3 , 0 , 0
       0     .06       0   318.4    .045       0   333.4     .06       0
Bank Sta=318.4,333.4
XS Rating Curve= 0 ,0
Exp/Cntr=0.3,0.1

Type RM Length L Ch R = 1 ,16208.3 ,371.3,372,372.5
XS GIS Cut Line= 2
     1667339.781      266323.414     1667858.081      265896.431
#Sta/Elev= 30
       0 1231.44    19.5 1217.61    29.2 1212.94    97.3 1175.41   126.5 1158.78
   136.2 1151.66   223.8 1104.93   233.6 1101.66     253 1089.88   272.5 1080.37
   282.2 1076.98   301.7 1074.42   321.2 1069.15   321.4 1069.15   330.9 1069.19
   336.4 1070.14   350.4 1073.94     399 1079.39   408.8 1082.43   418.5 1087.67
   447.7 1107.06   457.4 1112.71   467.2 1114.62   476.9 1115.38   486.6 1118.05
   564.5 1144.59   583.9 1155.98   603.4 1165.27   622.9 1175.89   671.5 1206.57
#Mann= 3 , 0 , 0
       0     .06       0   321.4    .045       0   336.4     .06       0
Bank Sta=321.4,336.4
XS Rating Curve= 0 ,0
Exp/Cntr=0.3,0.1

Type RM Length L Ch R = 1 ,15836.3 ,296.2,289.4,282.4
XS GIS Cut Line= 2
     1667600.994       266542.67     1668111.064      266143.527
#Sta/Elev= 30
       0 1150.29    58.9 1120.84    78.5 1109.31   137.4 1082.41     157  1074.9
   186.4 1071.28     265 1065.25   284.6 1064.65   316.8 1058.93   323.8 1057.89
   331.8 1058.14   333.6  1058.2   343.5 1064.61   363.1 1086.61   392.5  1117.3
   402.4 1129.43   412.2  1146.4   431.8 1160.55   451.4    1181     471 1199.21
   490.7 1214.66   510.3 1227.85   520.1 1236.92   529.9 1243.63   569.2 1260.78
   588.8 1268.33   618.2 1278.09     628 1281.95   637.9 1287.42   647.7 1290.52
#Mann= 3 , 0 , 0
       0     .08       0   316.8    .045       0   331.8     .08       0
Bank Sta=316.8,331.8
XS Rating Curve= 0 ,0
Exp/Cntr=0.3,0.1

Type RM Length L Ch R = 1 ,15547   ,338.2,325.8,313.1
XS GIS Cut Line= 2
     1667877.281      266811.753     1668243.975      266277.879
#Sta/Elev= 30
       0 1077.24     9.8 1077.88    49.1 1076.11    78.5 1075.83     157 1071.35
   215.9 1063.27   284.6 1062.17   294.4 1061.05     314  1048.2     322 1048.71
   323.8 1048.82   333.6 1055.51     337 1056.74   343.5  1059.1   353.3 1064.35
   412.2 1113.03     422 1120.16   431.8 1122.06   451.4 1142.84   480.8 1169.79
   510.3 1194.93   520.1 1199.98   529.9 1203.51   559.4 1228.43   569.2 1235.61
   588.8 1247.42   608.4 1261.18   618.2 1263.04     628 1266.31   647.7 1276.96
#Mann= 3 , 0 , 0
       0     .08       0     322    .045       0     337     .08       0
Bank Sta=322,337
XS Rating Curve= 0 ,0
Exp/Cntr=0.3,0.1

Type RM Length L Ch R = 1 ,15221.1 ,554,544.3,534.1
XS GIS Cut Line= 2
     1668365.702      266894.508     1668396.093      266247.544
#Sta/Elev= 30
       0 1094.87     9.8 1090.28    29.4 1085.84    68.7 1068.38    88.3 1062.63
   225.7 1052.24   274.8 1051.72   284.6 1050.86   305.5 1041.09     314 1040.72
   320.5 1043.41   333.6 1049.34   343.5 1050.95   382.7 1071.96   402.4 1085.45
   412.2 1090.95     422 1092.99   431.8 1101.32   451.4 1120.23   480.8 1153.01
   490.7 1161.72   500.5 1164.33   559.4 1237.58   569.2 1246.69     579 1248.81
   608.4 1280.11   618.2 1289.36     628 1297.31   637.9 1304.12   647.7 1308.54
#Mann= 3 , 0 , 0
       0     .08       0   305.5    .045       0   320.5     .08       0
Bank Sta=305.5,320.5
XS Rating Curve= 0 ,0
Exp/Cntr=0.3,0.1

Type RM Length L Ch R = 1 ,14676.8 ,373.3,373.4,373
XS GIS Cut Line= 2
     1669024.589      266868.296     1668739.226       266175.23
#Sta/Elev= 30
       0 1182.86    19.5 1170.69    29.2 1169.68    38.9 1164.53    68.1 1146.33
    97.3 1130.75   107.1    1126   116.8 1125.44   194.7 1083.02   214.2 1077.48
   253.1 1056.45   262.8 1052.74   282.3 1049.11   321.2  1045.1   360.2 1035.46
   366.9  1035.5   381.9 1035.84   457.5 1040.79   496.4 1040.99   506.2 1043.26
   515.9 1049.45   545.1 1072.61   554.8 1078.68   564.6  1080.7     584 1096.47
   613.2 1121.83   632.7 1142.85   652.2 1153.46   720.3 1223.02   749.5 1243.21
#Mann= 3 , 0 , 0
       0     .06       0   366.9    .045       0   381.9     .06       0
Bank Sta=366.9,381.9
XS Rating Curve= 0 ,0
Exp/Cntr=0.3,0.1

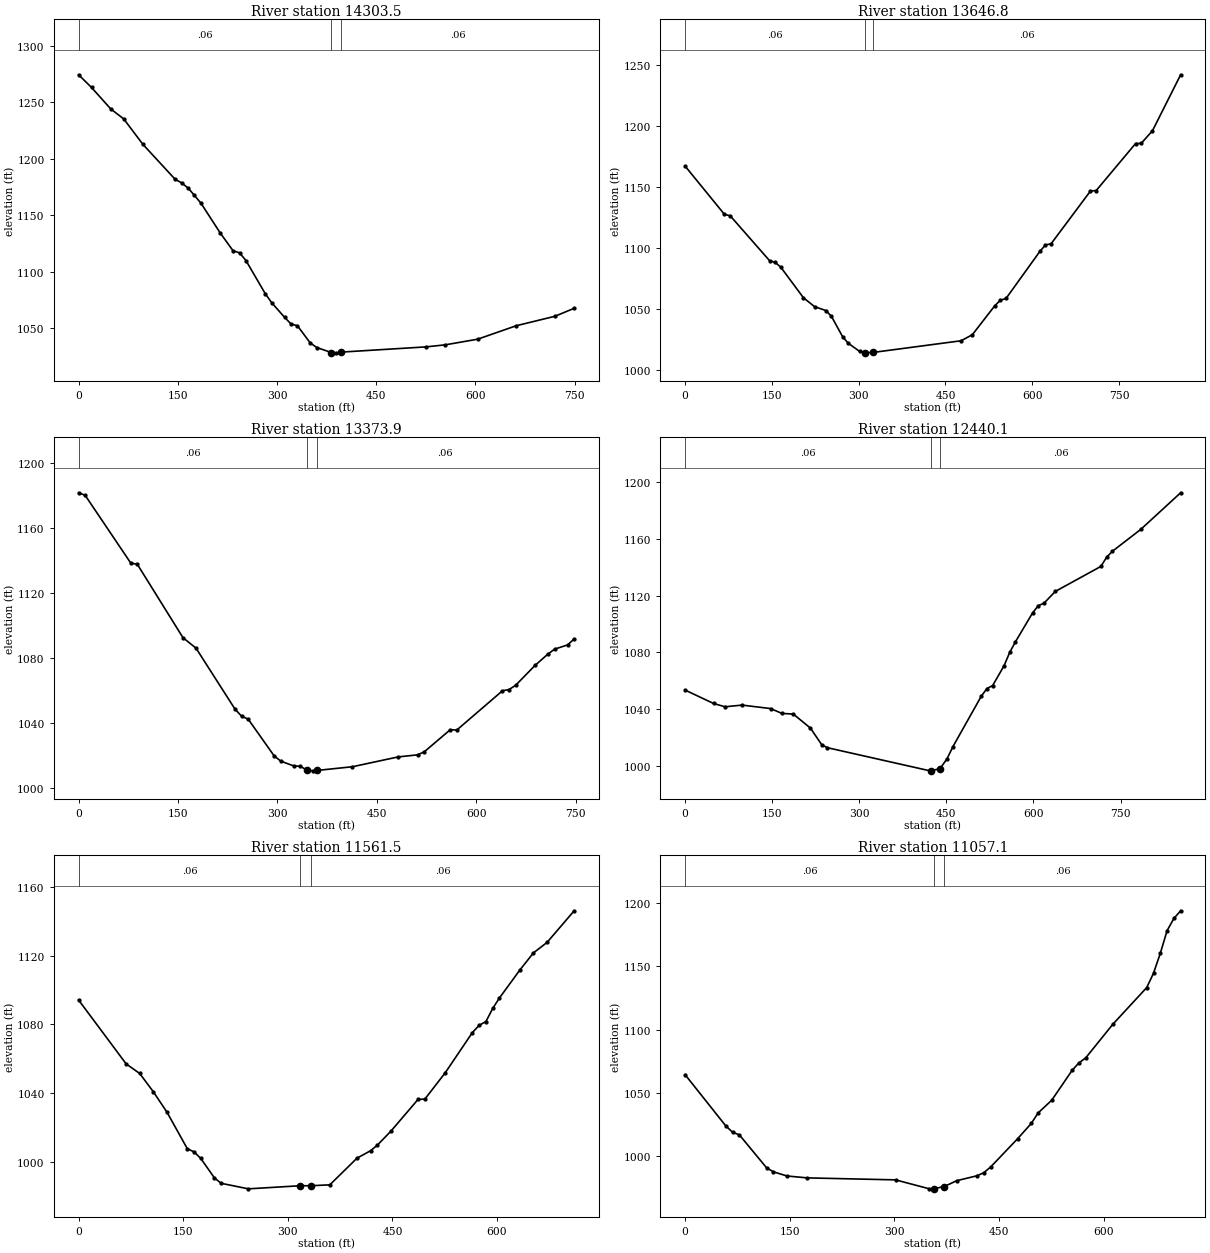
Type RM Length L Ch R = 1 ,14303.5 ,647.4,656.7,665.6
XS GIS Cut Line= 2
     1669375.052      266771.157     1669089.688      266078.091
#Sta/Elev= 30
       0 1274.53    19.5 1263.28    48.7 1244.21    68.1 1235.52    97.3 1212.88
     146 1181.96   155.7 1178.87   165.5 1174.26   175.2 1167.75     185 1160.84
   214.2 1134.44   233.6  1118.7   243.4  1116.9   253.1 1110.03   282.3  1080.7
     292 1072.71   311.5  1059.8   321.2 1053.96     331 1052.29   350.4 1037.02
   360.2 1033.07   382.2 1028.62   389.4 1028.35   397.2    1029   525.6 1033.63
   554.8 1035.46   603.5 1040.43   661.9 1052.35   720.3  1060.7   749.5 1067.78
#Mann= 3 , 0 , 0
       0     .06       0   382.2    .045       0   397.2     .06       0
Bank Sta=382.2,397.2
XS Rating Curve= 0 ,0
Exp/Cntr=0.3,0.1

Type RM Length L Ch R = 1 ,13646.8 ,266.7,272.9,278.6
XS GIS Cut Line= 2
     1669848.856       266584.96     1669860.688      265728.582
#Sta/Elev= 30
       0 1166.91    68.1 1127.24    77.9 1126.17     146  1089.3   155.7  1087.9
   165.4 1083.94   204.4 1058.95   223.8 1051.56   243.3 1048.38     253 1043.58
   272.5  1026.7   282.2 1021.47   301.7 1014.83   310.2 1013.82   311.4 1013.68
   325.2 1014.04   476.9 1023.58   496.4 1028.51   535.3 1052.32     545 1056.85
   554.8 1058.36   613.2 1096.92   622.9 1102.22   632.6 1103.18   700.7 1146.48
   710.5 1146.83   778.6 1185.42   788.3 1185.52   807.8 1195.92   856.5 1241.84
#Mann= 3 , 0 , 0
       0     .06       0   310.2    .045       0   325.2     .06       0
Bank Sta=310.2,325.2
XS Rating Curve= 0 ,0
Exp/Cntr=0.3,0.1

Type RM Length L Ch R = 1 ,13373.9 ,928.8,933.8,938.3
XS GIS Cut Line= 2
     1670027.259      266610.797     1670231.814      265891.737
#Sta/Elev= 30
       0 1181.77     9.8 1180.23    78.7 1138.44    88.5 1137.74   157.4 1092.51
   177.1 1086.03   236.1 1048.35   245.9 1044.12   255.8  1042.3   295.1 1019.59
   304.9 1016.45   324.6 1013.46   334.4 1013.26   343.9 1011.02   354.1 1010.45
   358.9 1010.66   413.1 1012.98     482 1019.03   511.5 1020.31   521.4 1022.16
   560.7 1035.79   570.5 1035.58   639.4 1059.78   649.2 1060.52   659.1 1063.07
   688.6 1075.43   708.2 1082.46   718.1 1085.43   737.8 1088.05   747.6 1091.76
#Mann= 3 , 0 , 0
       0     .06       0   343.9    .045       0   358.9     .06       0
Bank Sta=343.9,358.9
XS Rating Curve= 0 ,0
Exp/Cntr=0.3,0.1

Type RM Length L Ch R = 1 ,12440.1 ,880.8,878.6,876.1
XS GIS Cut Line= 2
     1670827.217      266755.866     1671225.315       266001.02
#Sta/Elev= 30
       0 1053.41      49 1043.99    68.7 1041.65    98.1 1042.84   147.1 1040.41
   166.8 1036.99   186.4 1036.52   215.8 1026.66   235.4 1014.87   245.2 1012.83
   421.8  996.55   424.2  996.65   439.2  998.15   451.2 1005.13     461  1013.4
   510.1 1049.13   519.9 1054.53   529.7 1056.62   549.3 1070.55   559.1 1080.01
   568.9 1087.42   598.4 1107.74   608.2 1112.86     618 1114.57   637.6  1122.9
   716.1 1140.51   725.9 1146.94   735.7 1151.11   784.7 1166.56   853.4 1192.35
#Mann= 3 , 0 , 0
       0     .06       0   424.2    .045       0   439.2     .06       0
Bank Sta=424.2,439.2
XS Rating Curve= 0 ,0
Exp/Cntr=0.3,0.1

Type RM Length L Ch R = 1 ,11561.5 ,503.3,504.4,505.4
XS GIS Cut Line= 2
     1671587.117      267203.582     1671848.386      266542.738
#Sta/Elev= 30
       0 1094.21    68.1 1057.02    87.6  1051.4   107.1 1040.76   126.6 1028.91
   155.8 1007.59   165.5  1005.7   175.2 1001.85   194.7  990.55   204.4  987.38
   243.4  984.16   317.9  985.97   332.9  985.97   360.2  986.49   399.1 1002.02
   418.6 1006.37   428.3 1009.61   447.8 1017.78   486.7 1036.29   496.5 1036.47
   525.7 1051.83   564.6 1075.24   574.3 1079.46   584.1 1081.71   593.8 1089.34
   603.5 1095.45   632.7 1111.73   652.2 1121.72   671.7 1127.81   710.6 1146.26
#Mann= 3 , 0 , 0
       0     .06       0   317.9    .045       0   332.9     .06       0
Bank Sta=317.9,332.9
XS Rating Curve= 0 ,0
Exp/Cntr=0.3,0.1

Type RM Length L Ch R = 1 ,11057.1 ,320.6,309.6,298.6
XS GIS Cut Line= 2
     1672019.733      267381.625     1672310.178      266733.073
#Sta/Elev= 30
       0 1064.41    58.4 1023.92    68.1 1018.97    77.9 1016.83   116.8  990.89
   126.6   987.7     146  984.41   175.2   982.9   301.8  981.33   350.4  974.25
   356.8  974.39   371.8  976.09   389.4  980.67   418.6  984.57   428.3  986.97
     438  991.43     477 1013.93   496.5 1025.95   506.2 1034.19   525.7  1044.2
   554.9 1067.75   564.6 1073.66   574.3 1077.55   613.3 1104.17     662 1133.22
   671.7 1144.53   681.4 1160.17   691.2 1178.19   700.9 1187.79   710.6 1193.84
#Mann= 3 , 0 , 0
       0     .06       0   356.8    .045       0   371.8     .06       0
Bank Sta=356.8,371.8
XS Rating Curve= 0 ,0
Exp/Cntr=0.3,0.1

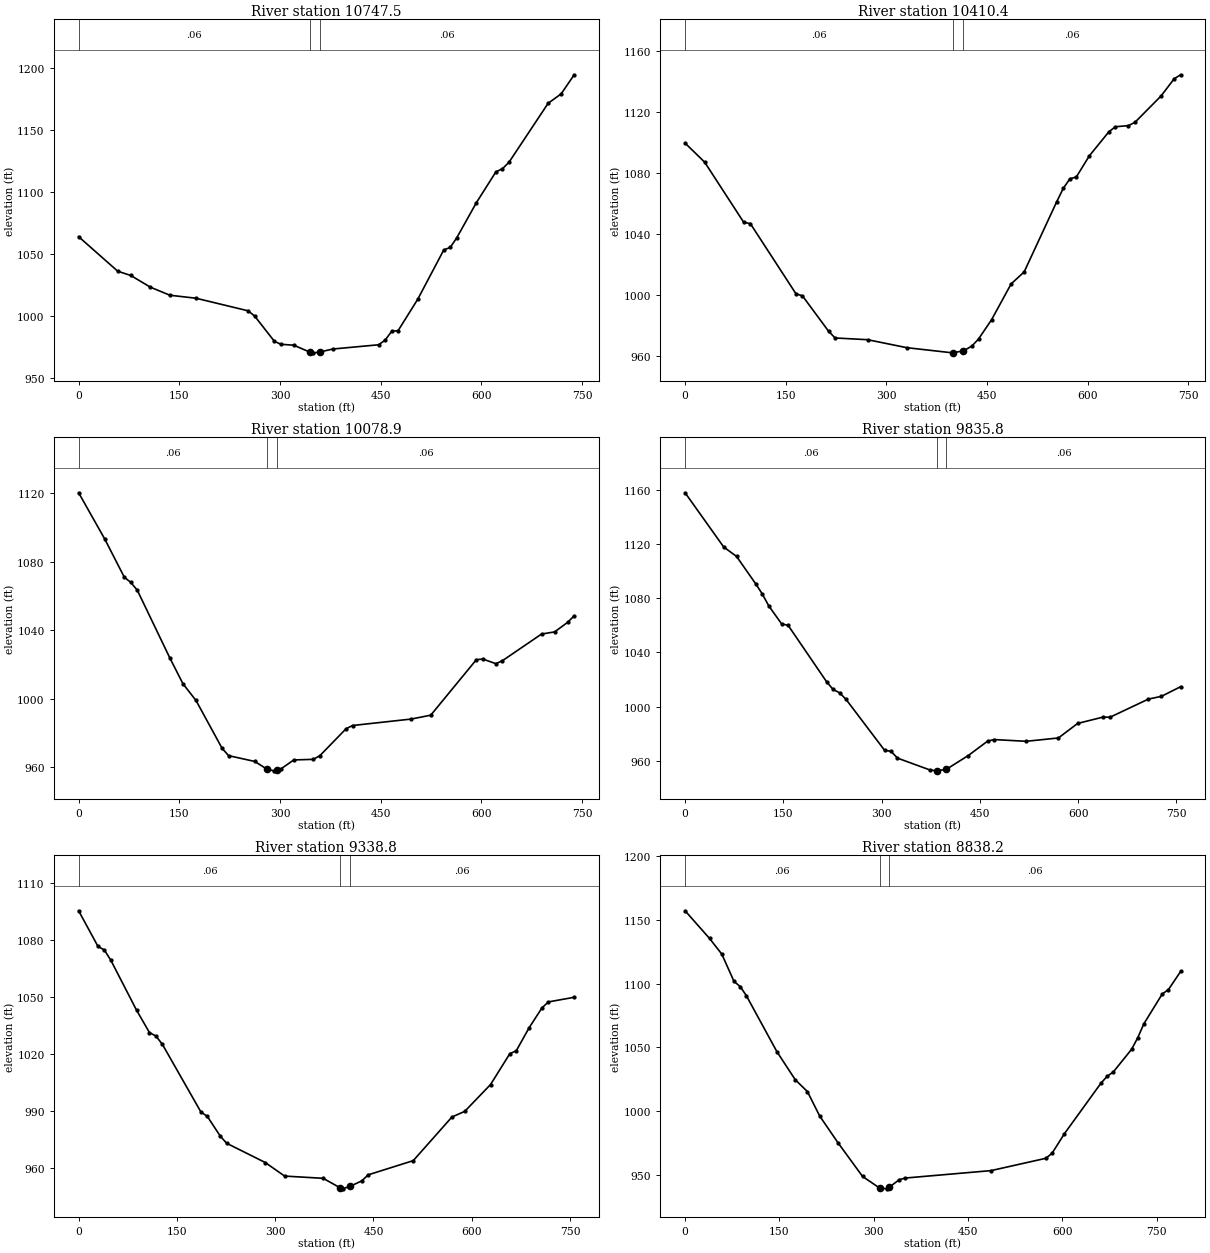
Type RM Length L Ch R = 1 ,10747.5 ,330.4,337.1,343.9
XS GIS Cut Line= 2
      1672473.81      267502.552     1672423.273       266765.85
#Sta/Elev= 30
       0  1063.9    58.3 1036.05    77.7 1032.63   106.9 1023.19     136  1016.7
   174.9 1014.28   252.6 1004.12   262.3   999.9   291.5  979.66   301.2  977.16
   320.6   976.4   344.1  970.93   349.8  970.25   359.1  970.89   378.9  973.34
     447  976.75   456.7  980.51   466.4  987.56   476.1  988.18   505.2 1013.36
   544.1  1053.2   553.8 1055.28   563.5 1063.04   592.7 1091.35   621.8 1116.18
   631.6 1118.71   641.3 1123.93   699.6 1171.46     719 1179.04   738.4 1194.44
#Mann= 3 , 0 , 0
       0     .06       0   344.1    .045       0   359.1     .06       0
Bank Sta=344.1,359.1
XS Rating Curve= 0 ,0
Exp/Cntr=0.3,0.1

Type RM Length L Ch R = 1 ,10410.4 ,323.8,331.5,339.1
XS GIS Cut Line= 2
     1672691.033      267543.666     1672857.738      266824.296
#Sta/Elev= 30
       0 1099.52    29.2    1087    87.4 1047.55    97.2 1046.76   165.2 1000.73
   174.9  999.36   213.8  976.18   223.5  971.76     272  970.62   330.4  965.39
   398.4  962.01   399.7  962.15   414.7  963.25   427.5  966.53   437.2  971.06
   456.7  983.73   485.8 1007.21   505.2 1015.05   553.8 1061.13   563.5 1069.82
   573.3 1076.09     583 1077.34   602.4  1091.2   631.6 1107.02   641.3 1110.25
   660.7 1110.98   670.4 1113.18   709.3 1130.46   728.7 1141.68   738.4 1144.32
#Mann= 3 , 0 , 0
       0     .06       0   399.7    .045       0   414.7     .06       0
Bank Sta=399.7,414.7
XS Rating Curve= 0 ,0
Exp/Cntr=0.3,0.1

Type RM Length L Ch R = 1 ,10078.9 ,248.1,243.2,238.2
XS GIS Cut Line= 2
     1672871.042       267608.28     1673265.914      266984.293
#Sta/Elev= 30
       0 1120.12    38.9 1093.17      68 1070.97    77.7 1067.86    87.4 1063.34
     136 1023.77   155.5 1008.77   174.9  999.06   213.8  971.16   223.5   966.9
   262.3  963.54   281.3  958.89   291.5  958.05   296.3  958.58   301.2  959.12
   320.6   964.4   349.8  964.75   359.5   966.9   398.4  982.55   408.1  984.47
   495.5  988.23   524.7  990.49   592.7 1022.86   602.4 1023.19   621.8  1020.5
   631.6 1022.27   689.8 1037.79   709.3 1039.03   728.7 1044.62   738.4 1048.41
#Mann= 3 , 0 , 0
       0     .06       0   281.3    .045       0   296.3     .06       0
Bank Sta=281.3,296.3
XS Rating Curve= 0 ,0
Exp/Cntr=0.3,0.1

Type RM Length L Ch R = 1 ,9835.8  ,501.9,496.9,491.4
XS GIS Cut Line= 2
     1673127.241      267784.684      1673383.17      267072.903
#Sta/Elev= 30
       0 1157.79    58.9 1117.79    78.6 1110.79   108.1 1090.36   117.9 1083.04
   127.7 1074.32   147.4 1060.98   157.2 1059.99   216.1 1018.23   225.9 1012.63
   235.8 1010.17   245.6 1005.34   304.5  967.72   314.4  966.95   324.2  961.95
   373.3  953.27   383.1  952.56   383.9  952.56   398.9  953.71   432.2  963.84
   461.7  974.46   471.5  975.65   520.6  974.36   569.8  976.82   599.2  987.55
   638.5  992.29   648.3  992.06   707.3 1005.53   726.9 1007.52   756.4 1014.66
#Mann= 3 , 0 , 0
       0     .06       0   383.9    .045       0   398.9     .06       0
Bank Sta=383.9,398.9
XS Rating Curve= 0 ,0
Exp/Cntr=0.3,0.1

Type RM Length L Ch R = 1 ,9338.8  ,487.6,500.6,513.4
XS GIS Cut Line= 2
     1673672.432      267953.558     1673761.297      267202.402
#Sta/Elev= 30
       0 1095.14    29.5 1076.43    39.3  1074.5    49.1 1069.17    88.4 1042.89
   108.1 1031.12   117.9  1029.3   127.7 1025.01   186.6   989.4   196.5  987.02
   216.1  976.74   225.9  972.93   284.9   962.8   314.4  955.68   373.3   954.5
   399.2   949.5   402.8  948.97   414.2  950.27   432.2  953.15     442  956.33
   510.8   963.8   569.8  986.73   589.4   989.7   628.7 1003.78   658.2 1020.03
     668 1021.53   687.6 1033.62   707.3 1044.12   717.1 1047.23   756.4 1049.67
#Mann= 3 , 0 , 0
       0     .06       0   399.2    .045       0   414.2     .06       0
Bank Sta=399.2,414.2
XS Rating Curve= 0 ,0
Exp/Cntr=0.3,0.1

Type RM Length L Ch R = 1 ,8838.2  ,209.3,208.5,207.6
XS GIS Cut Line= 2
     1673752.635      268155.938     1674263.264      267555.472
#Sta/Elev= 30
       0 1157.23    38.9  1135.5    58.4  1123.2    77.8  1101.8    87.6 1097.77
    97.3 1090.73     146 1046.68   175.2 1024.66   194.6 1015.32   214.1  996.12
   243.3  975.11   282.2  948.78   309.3  939.65   321.1  939.01   324.3  940.08
   340.6   946.2   350.3  947.49   486.6  953.31   574.1  963.01   583.9  967.08
   603.3  982.26   661.7 1022.08   671.4 1027.34   681.2 1030.79   710.4 1048.65
   720.1 1057.73   729.8 1068.61     759 1091.94   768.8 1095.38   788.2 1109.61
#Mann= 3 , 0 , 0
       0     .06       0   309.3    .045       0   324.3     .06       0
Bank Sta=309.3,324.3
XS Rating Curve= 0 ,0
Exp/Cntr=0.3,0.1

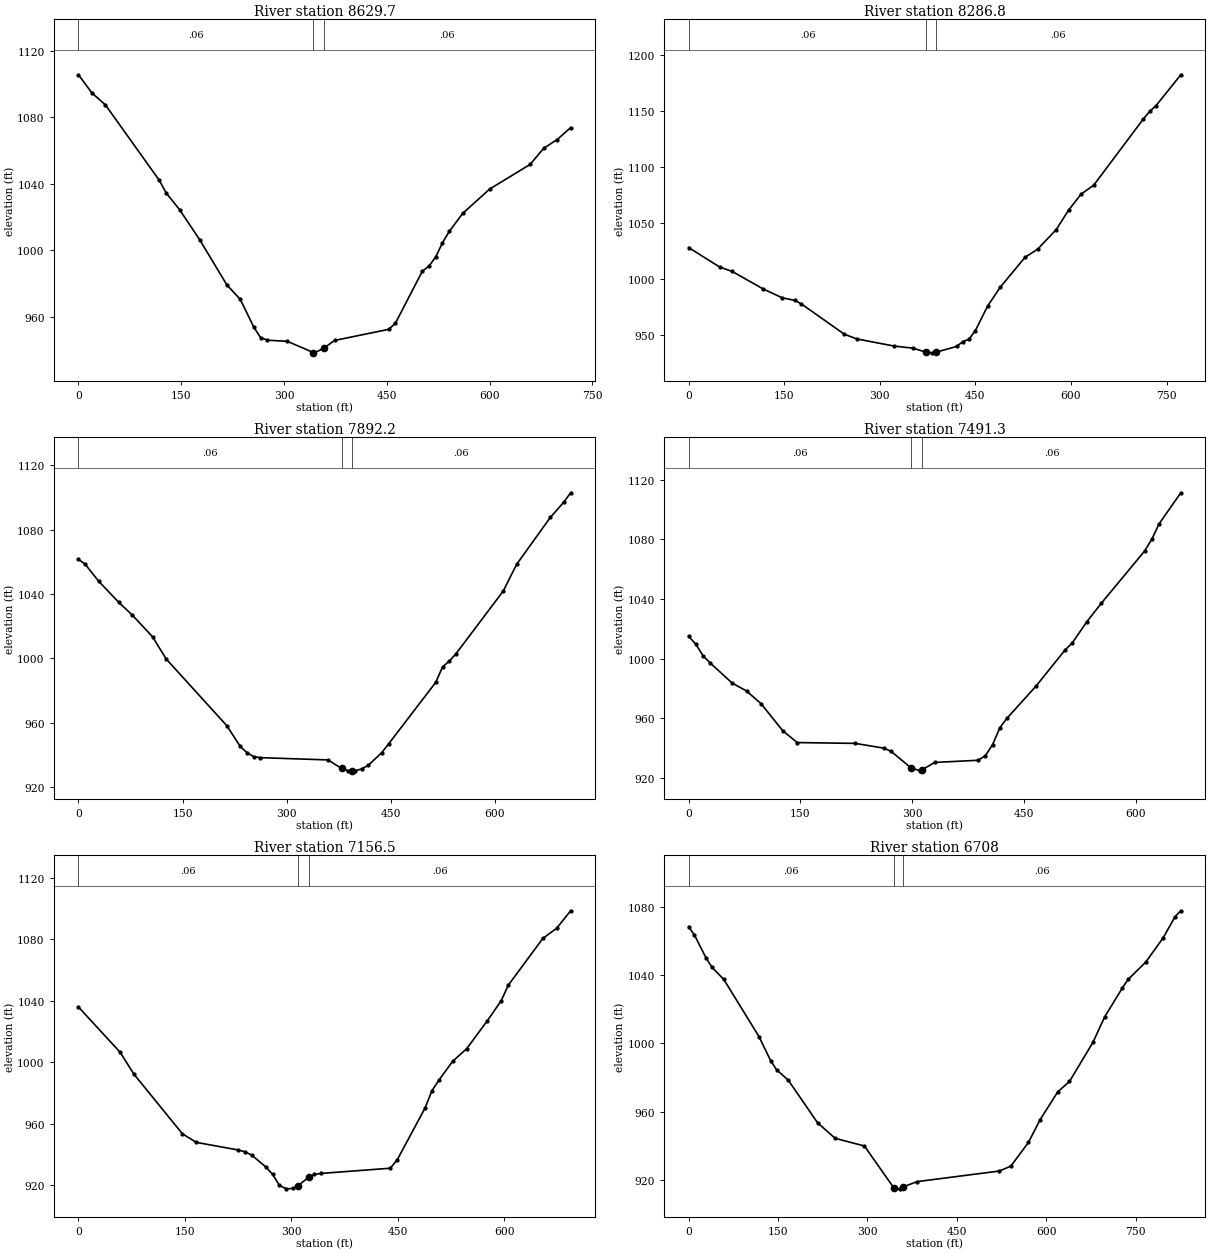
Type RM Length L Ch R = 1 ,8629.7  ,342.3,342.9,342.8
XS GIS Cut Line= 2
     1673923.796      268287.519     1674367.836      267722.937
#Sta/Elev= 30
       0 1105.47    19.7 1094.52    39.4 1087.32   118.1  1041.9   127.9 1034.44
   147.6 1024.31   177.1 1006.12   216.5  979.11   236.2  970.36   255.8  953.74
   265.7  947.41   275.5  945.83     305   945.1   342.8   938.4   344.4   938.2
   357.8  940.92   373.9  945.67   452.6  952.32   462.4  955.89   501.8  987.25
   511.6  990.44   521.5  995.92   531.3 1004.48   541.2 1011.25   560.8 1022.08
   600.2 1036.75   659.2 1051.54   678.9 1061.21   698.6 1066.48   718.3 1073.67
#Mann= 3 , 0 , 0
       0     .06       0   342.8    .045       0   357.8     .06       0
Bank Sta=342.8,357.8
XS Rating Curve= 0 ,0
Exp/Cntr=0.3,0.1

Type RM Length L Ch R = 1 ,8286.8  ,384.2,394.6,404.5
XS GIS Cut Line= 2
     1674188.499      268483.691     1674672.228      267881.476
#Sta/Elev= 30
       0 1028.32    48.9 1010.87    68.4 1007.01   117.3   991.3   146.7  983.55
   166.2  981.23     176  978.41   244.4  950.99     264  946.82   322.7  940.44
     352  938.59   372.7  934.97   381.3  934.42   387.7  934.92   420.4  940.08
   430.2  944.38     440  946.63   449.8  954.04   469.3  976.22   488.9  992.85
     528 1019.66   547.6  1026.8   576.9 1044.35   596.4 1061.75     616    1076
   635.6 1083.85   713.8 1143.12   723.6 1149.74   733.3  1154.7   772.4 1182.39
#Mann= 3 , 0 , 0
       0     .06       0   372.7    .045       0   387.7     .06       0
Bank Sta=372.7,387.7
XS Rating Curve= 0 ,0
Exp/Cntr=0.3,0.1

Type RM Length L Ch R = 1 ,7892.2  ,401.9,400.9,400.2
XS GIS Cut Line= 2
     1674321.289      268634.554     1674962.541      268332.134
#Sta/Elev= 30
       0 1061.55     9.7 1058.48    29.1 1047.95    58.3 1034.75    77.7 1026.91
   106.8 1013.43   126.3  999.73   213.7   958.3   233.1  945.41   242.8  941.57
   252.5  939.07   262.2  938.47   359.4  937.05   379.2  931.74   388.5  930.36
   394.2  930.31   398.2  930.28   407.9  931.44   417.6  933.75     437   941.6
   446.8     947   514.7   985.2   524.5  994.76   534.2  998.41   543.9 1002.97
   611.9 1041.84   631.3 1058.47   679.8 1087.57   699.3 1097.06     709 1102.84
#Mann= 3 , 0 , 0
       0     .06       0   379.2    .045       0   394.2     .06       0
Bank Sta=379.2,394.2
XS Rating Curve= 0 ,0
Exp/Cntr=0.3,0.1

Type RM Length L Ch R = 1 ,7491.3  ,337.2,334.8,332.3
XS GIS Cut Line= 2
     1674561.308      268972.538     1675148.226      268668.957
#Sta/Elev= 30
       0    1015     9.7 1009.67    19.4 1001.88    29.2  996.96    58.3  983.64
    77.7  978.29    97.2  969.77   126.3  951.62   145.8  943.65   223.5   943.1
   262.4  939.89   272.1  937.66   298.9  926.51     311  924.67   313.9  925.56
   330.4  930.31   388.7  931.77   398.4  934.85   408.1  942.27   417.8   953.6
   427.6   960.1   466.4  981.54   505.3 1005.76     515 1010.52   534.5 1024.69
   553.9 1037.07   612.2 1072.26   621.9 1080.18   631.6 1090.49   660.8 1111.36
#Mann= 3 , 0 , 0
       0     .06       0   298.9    .045       0   313.9     .06       0
Bank Sta=298.9,313.9
XS Rating Curve= 0 ,0
Exp/Cntr=0.3,0.1

Type RM Length L Ch R = 1 ,7156.5  ,450.9,448.5,444.9
XS GIS Cut Line= 2
     1674744.648      269289.989     1675321.184      268904.284
#Sta/Elev= 30
       0 1035.82    58.6 1006.47    78.2  992.13   146.6  953.32   166.1  947.79
   224.7  942.87   234.5  941.73   244.2   939.5   263.8  931.94   273.6  927.02
   283.3  919.81   293.1  917.57   302.9  917.83   309.5  919.65   324.5  925.12
   332.2  926.92   341.9   927.6   439.6  930.98   449.4  936.55   488.5   970.1
   498.3  981.44     508  988.25   527.6 1000.61   547.1 1008.67   576.4 1026.93
     596 1040.02   605.7 1049.93   654.6 1080.45   674.1 1087.08   693.7  1098.4
#Mann= 3 , 0 , 0
       0     .06       0   309.5    .045       0   324.5     .06       0
Bank Sta=309.5,324.5
XS Rating Curve= 0 ,0
Exp/Cntr=0.3,0.1

Type RM Length L Ch R = 1 ,6708    ,783.2,783.9,784.2
XS GIS Cut Line= 2
     1675016.427      269639.376     1675663.881      269126.752
#Sta/Elev= 30
       0 1068.61     9.8 1063.71    29.5  1050.1    39.3 1044.75      59 1037.66
     118 1004.06   137.6   989.9   147.5  984.55   167.1  978.46   216.3  953.38
   245.8  944.24   294.9  939.73   344.7  914.91   353.9  914.54   359.7  915.68
   383.4  918.79     521  924.99   540.7  927.91   570.2  941.86   589.9   955.3
   619.4  971.59     639  977.65   678.4 1000.68     698  1015.6   727.5 1032.51
   737.3 1037.64   766.8 1047.79   796.3 1062.14     816 1074.48   825.8 1078.02
#Mann= 3 , 0 , 0
       0     .06       0   344.7    .045       0   359.7     .06       0
Bank Sta=344.7,359.7
XS Rating Curve= 0 ,0
Exp/Cntr=0.3,0.1

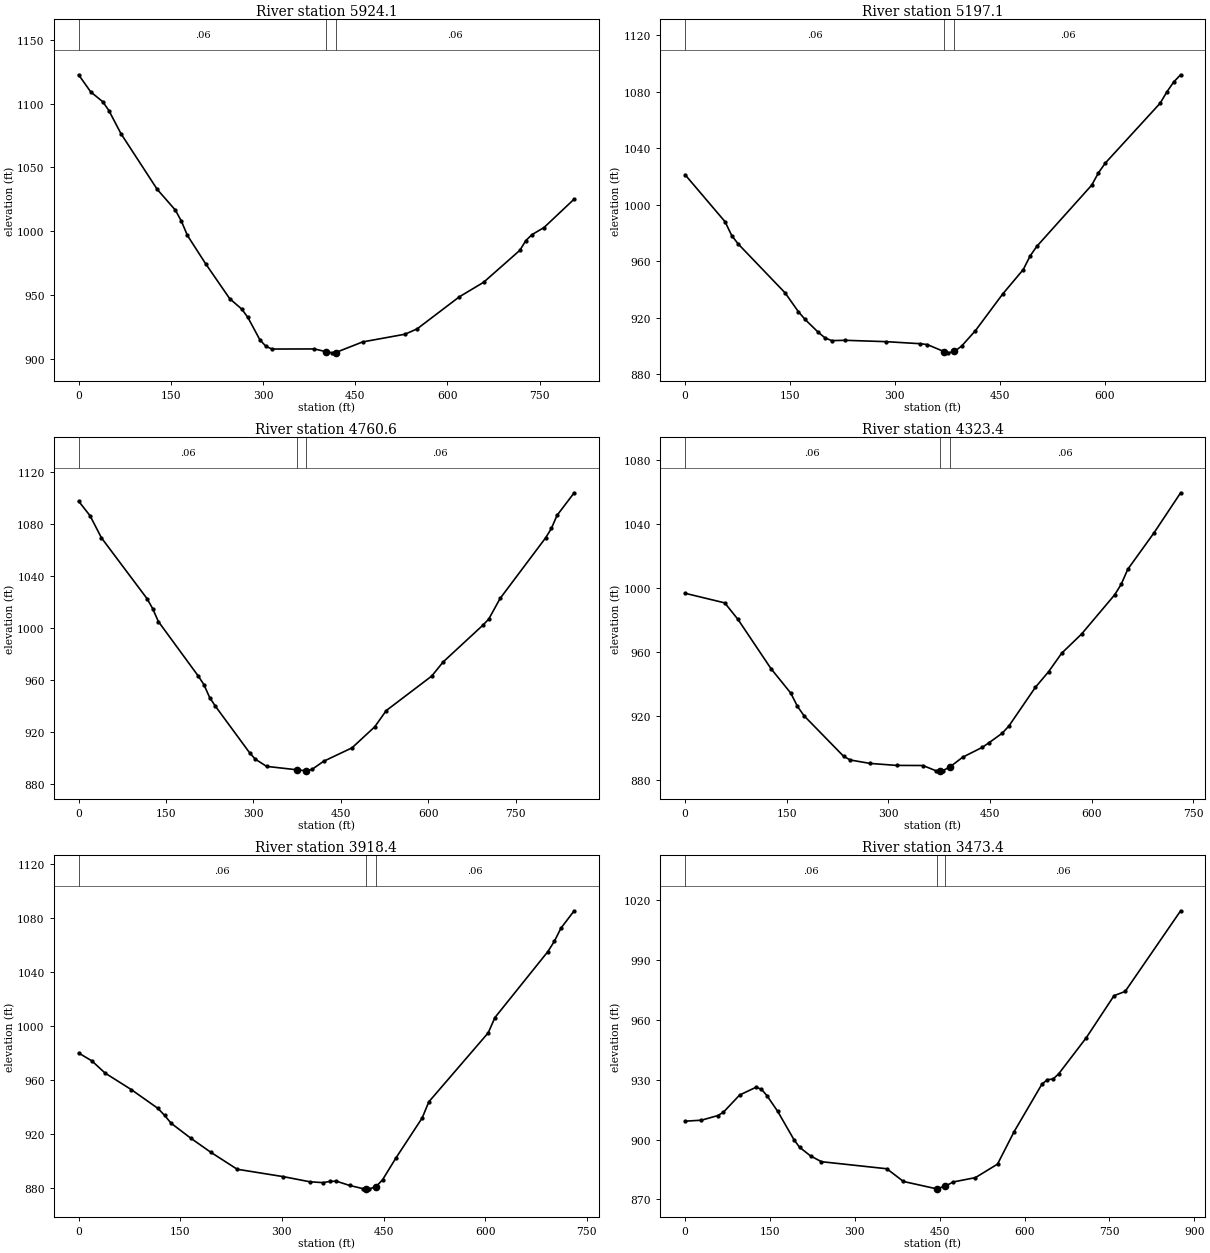
Type RM Length L Ch R = 1 ,5924.1  ,696.6,727,756.7
XS GIS Cut Line= 2
     1675521.295       270138.89     1676163.518      269651.661
#Sta/Elev= 30
       0 1122.72    19.7 1109.26    39.3 1101.56    49.2 1094.67    68.8 1076.55
   127.8 1032.82   157.3 1016.55   167.1  1007.9     177  996.61   206.4  974.57
   245.8  946.99   265.4  938.82   275.3  932.29   294.9  914.67   304.8  909.56
   314.6  907.48   383.4  907.56   402.9  905.35   412.9   904.5   417.9  904.69
     462  913.07   530.9  919.11   550.5  923.27   619.3  948.47   658.7  959.84
   717.6   984.9   727.5   992.6   737.3  997.22     757 1002.82   806.1 1025.16
#Mann= 3 , 0 , 0
       0     .06       0   402.9    .045       0   417.9     .06       0
Bank Sta=402.9,417.9
XS Rating Curve= 0 ,0
Exp/Cntr=0.3,0.1

Type RM Length L Ch R = 1 ,5197.1  ,449.4,436.4,423.5
XS GIS Cut Line= 4
     1675741.272      270470.775     1675979.613      270477.516
     1676122.668      270581.279     1676415.758      270599.248
#Sta/Elev= 30
       0 1021.39    57.2  988.08    66.8   978.2    76.3  972.18   143.1   937.7
   162.1  924.36   171.7  918.87   190.8  909.67   200.3  905.79   209.8   903.9
   228.9  904.14   287.5  903.18   336.6  901.72   346.4  901.13   370.3  896.16
   375.9  895.26   385.3  896.29   395.5  900.04   415.2  910.92   454.3  936.94
   483.7  954.24   493.5  963.85   503.2  970.74   581.6 1014.01   591.3 1022.79
   601.1 1029.67   679.4 1071.97   689.2 1080.09     699 1087.14   708.8 1092.16
#Mann= 3 , 0 , 0
       0     .06       0   370.3    .045       0   385.3     .06       0
Bank Sta=370.3,385.3
XS Rating Curve= 0 ,0
Exp/Cntr=0.3,0.1

Type RM Length L Ch R = 1 ,4760.6  ,439.3,437.3,435.2
XS GIS Cut Line= 2
     1675538.529      270897.746     1676382.244       271003.04
#Sta/Elev= 30
       0 1097.49    19.6 1086.28    39.1 1069.29   117.3 1022.48     127 1014.81
   136.8 1004.84   205.2   962.9     215  956.24   224.8   946.3   234.6  939.68
   293.2  903.86     303   898.9   322.5  893.29     375  890.63     390  889.88
   390.9  889.85   400.7  891.02   420.2  897.17   469.1  907.56   508.2  923.81
   527.8  936.25   605.9  962.84   625.5   973.7   693.9  1002.1   703.7  1006.7
   723.2 1022.58   801.4 1069.32   811.2 1076.49   820.9 1086.58   850.3 1103.96
#Mann= 3 , 0 , 0
       0     .06       0     375    .045       0     390     .06       0
Bank Sta=375,390
XS Rating Curve= 0 ,0
Exp/Cntr=0.3,0.1

Type RM Length L Ch R = 1 ,4323.4  ,404.8,405,404.8
XS GIS Cut Line= 2
     1675552.717      271364.388     1676283.612      271388.601
#Sta/Elev= 30
       0  996.53    58.5  990.53      78  980.21   126.8  949.38     156  934.06
   165.8  925.81   175.5  919.95     234  894.55   243.8  892.26     273  890.12
     312  888.88     351  888.81   370.5  885.48   375.5  885.55   380.3  885.62
   390.5  887.81   409.5  893.96   438.8  900.23   448.5  903.05     468  909.01
   477.8  913.49   516.8  937.65   536.3   947.4   555.8  959.07     585  970.99
   633.8   995.5   643.5  1002.1   653.3 1011.55   692.3 1034.52   731.3 1059.39
#Mann= 3 , 0 , 0
       0     .06       0   375.5    .045       0   390.5     .06       0
Bank Sta=375.5,390.5
XS Rating Curve= 0 ,0
Exp/Cntr=0.3,0.1

Type RM Length L Ch R = 1 ,3918.4  ,448,445,441.6
XS GIS Cut Line= 2
     1675539.473      271764.168     1676270.368      271788.381
#Sta/Elev= 30
       0  979.94    19.5  974.12      39  965.08      78  952.72     117  938.88
   126.8  933.71   136.5  927.85   165.8  916.65     195  906.35     234  893.73
   302.3  888.23   341.3  884.42   360.8   883.8   370.5   884.7   380.3  884.89
   399.8  881.73   419.3  879.38   423.7   879.3     429   879.2   438.7  880.72
   448.5   885.9     468  901.89     507  931.78   516.8  943.73   604.5  994.95
   614.3 1006.22   692.3 1055.05     702 1062.74   711.8 1072.55   731.3 1085.44
#Mann= 3 , 0 , 0
       0     .06       0   423.7    .045       0   438.7     .06       0
Bank Sta=423.7,438.7
XS Rating Curve= 0 ,0
Exp/Cntr=0.3,0.1

Type RM Length L Ch R = 1 ,3473.4  ,857.9,826.7,794.7
XS GIS Cut Line= 4
     1675491.696      272252.039     1675847.084      272222.573
     1676041.719      272202.251     1676308.031      272018.214
#Sta/Elev= 30
       0  909.27    28.9  909.76    57.8  912.08    67.5   913.7    96.4  922.38
   125.3  926.27   134.9   925.3   144.6  922.11   163.8  914.14   192.8  899.83
   202.4  896.19   221.7  891.86     241  888.95   356.6  885.41     386  879.03
   444.7  875.34   445.2  875.37   460.2  876.72     474  878.79   513.2  880.96
   552.3  887.74   581.7  904.04   630.8  927.85   640.6  930.09   650.4   930.4
   660.2  932.93   709.2  951.12   758.3  972.22   777.9  974.32     876 1014.78
#Mann= 3 , 0 , 0
       0     .06       0   445.2    .045       0   460.2     .06       0
Bank Sta=445.2,460.2
XS Rating Curve= 0 ,0
Exp/Cntr=0.3,0.1