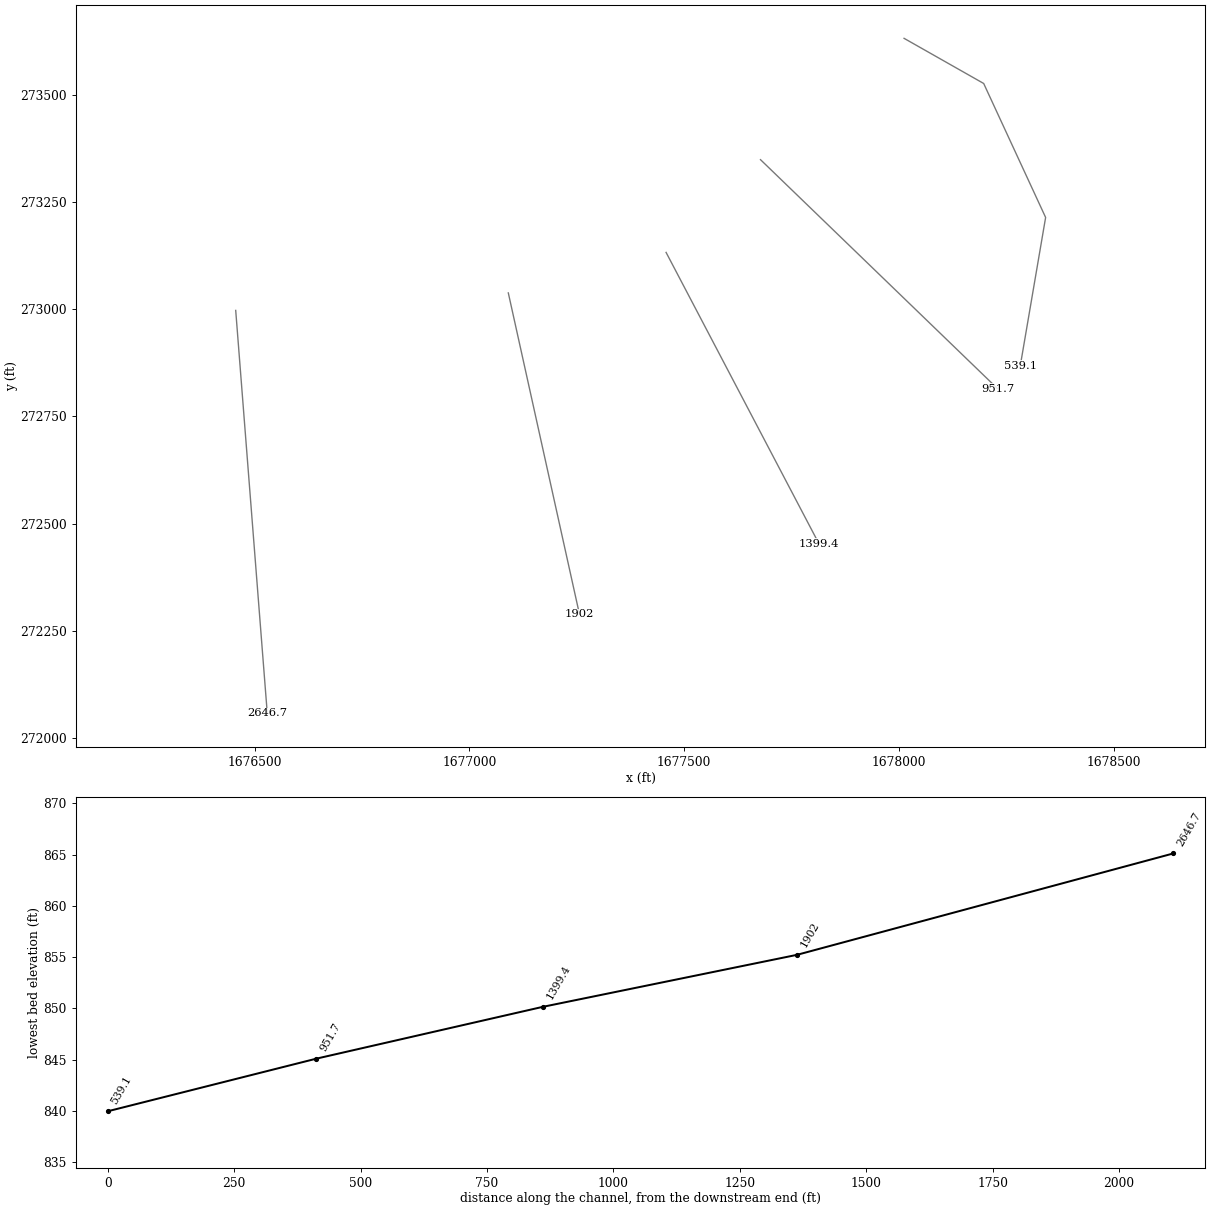
HEC-RAS study COWCRK.prj: COWCRK

--- COWCRK.g01 (geometry) --- (continued)

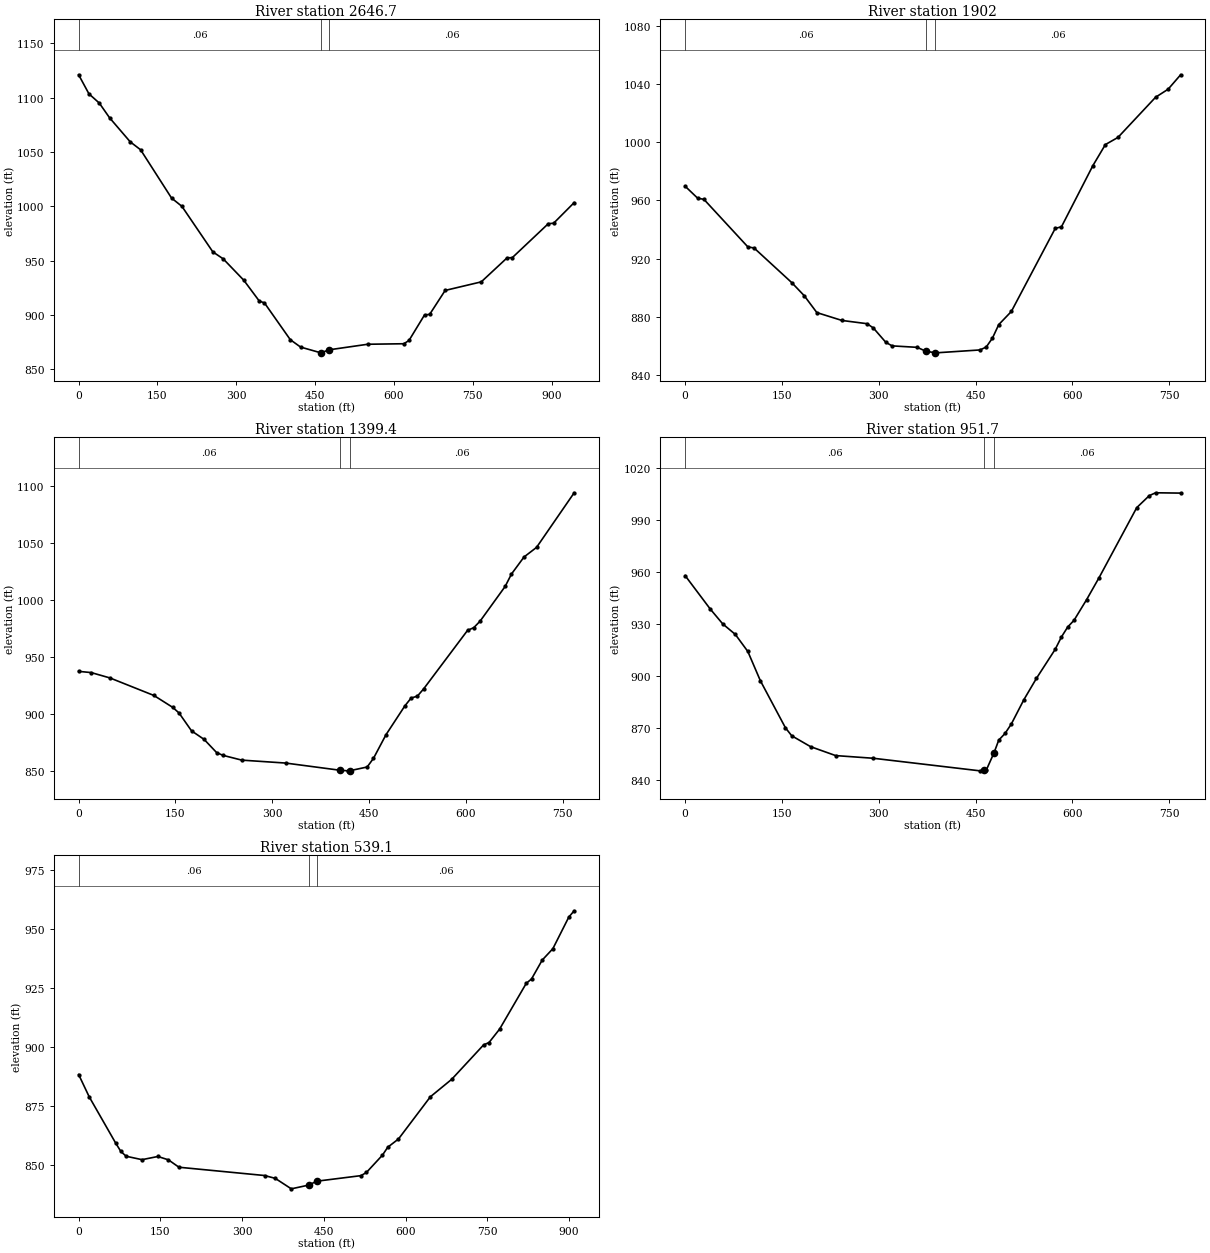
Type RM Length L Ch R = 1 ,2646.7  ,741.5,744.6,747.4
XS GIS Cut Line= 2
     1676456.021      272997.204     1676529.508       272057.02
#Sta/Elev= 30
       0 1120.98    19.6 1103.45    39.3 1094.95    58.9  1081.4    98.2 1059.26
   117.9 1051.98   176.8 1007.55   196.5  999.94   255.4  958.02   275.1  951.61
   314.4  931.87   343.8  912.75   353.6  911.07   402.8  877.21   422.4  870.42
   460.8  865.15   461.7  865.12   475.8  867.85   550.1  873.02   618.9  873.49
   628.7  876.52   658.2  899.96     668  900.51   697.5  922.55   766.2  930.43
   815.4  952.55   825.2  952.69   893.9  984.02   903.8  984.34     943 1003.36
#Mann= 3 , 0 , 0
       0     .06       0   460.8    .045       0   475.8     .06       0
Bank Sta=460.8,475.8
XS Rating Curve= 0 ,0
Exp/Cntr=0.3,0.1

Type RM Length L Ch R = 1 ,1902    ,496.4,502.7,508.8
XS GIS Cut Line= 2
     1677090.699      273038.037      1677256.36      272288.387
#Sta/Elev= 30
       0  969.83    19.4   961.6    29.2  960.77    97.2   928.1   106.9  927.32
   165.2  903.53   184.6  894.51   204.1  882.91     243   877.5   281.8  875.28
   291.6  872.35     311  862.44   320.7  860.02   359.6  859.01   372.8  856.36
   387.8  855.25   388.7  855.23   456.8  857.22   466.5  859.21   476.2   865.4
   485.9  874.64   505.4  883.66   573.4  940.78   583.1  941.94   631.7  983.94
   651.1  998.45   670.6 1003.37   728.9    1031   748.3 1036.52   767.7 1046.45
#Mann= 3 , 0 , 0
       0     .06       0   372.8    .045       0   387.8     .06       0
Bank Sta=372.8,387.8
XS Rating Curve= 0 ,0
Exp/Cntr=0.3,0.1

Type RM Length L Ch R = 1 ,1399.4  ,440.3,447.7,454.7
XS GIS Cut Line= 2
     1677458.064      273132.543     1677814.218      272452.416
#Sta/Elev= 30
       0  937.34    19.4  936.28    48.6  931.56   116.6  916.22   145.8  905.77
   155.5  900.89   174.9  885.21   194.4  877.71   213.8  866.15   223.5  863.76
   252.7  859.55   320.7  856.98     405  850.67   417.9  850.16     420  850.26
     447  853.52   456.8  861.13   476.2  881.84   505.4  907.08   515.1  913.96
   524.8  915.62   534.5  921.99   602.5  973.24   612.2  975.66     622  981.38
   660.8 1011.79   670.6 1022.68     690 1037.57   709.4 1045.98   767.7 1093.85
#Mann= 3 , 0 , 0
       0     .06       0     405    .045       0     420     .06       0
Bank Sta=405,420
XS Rating Curve= 0 ,0
Exp/Cntr=0.3,0.1

Type RM Length L Ch R = 1 ,951.7   ,421.3,412.6,403.9
XS GIS Cut Line= 2
     1677677.876      273348.954       1678229.5       272814.98
#Sta/Elev= 30
       0     958    38.9  938.68    58.3  930.06    77.8  923.98    97.2  914.11
   116.6  897.21   155.5  869.96   165.2  865.38   194.4  859.09   233.2  853.93
   291.6  852.38   456.8  845.11   463.7  845.37   466.5  845.47   478.7  855.63
   485.9  862.86   495.6   866.7   505.4  872.18   524.8  886.21   544.2  898.51
   573.4  915.38   583.1  922.55   592.8  928.29   602.5  932.12     622  944.06
   641.4  956.83   699.7  997.27   719.1  1004.2   728.9 1005.86   767.7 1005.67
#Mann= 3 , 0 , 0
       0     .06       0   463.7    .045       0   478.7     .06       0
Bank Sta=463.7,478.7
XS Rating Curve= 0 ,0
Exp/Cntr=0.3,0.1

Type RM Length L Ch R = 1 ,539.1   ,535.9,539.1,542
XS GIS Cut Line= 4
     1678012.135      273632.033     1678197.495      273526.713
     1678341.724      273214.119     1678282.588      272867.389
#Sta/Elev= 30
       0  888.46    19.4     879    67.8  859.45    77.5  855.83    87.2   853.8
   116.3  852.35   145.4   853.7   164.7  852.28   184.1  849.14   341.1  845.63
   360.7  844.43   390.2  839.98   421.9  841.56   436.9  843.22   518.1  845.58
     528  846.92   557.4  854.26   567.2  857.64   586.8  861.11   645.4  879.03
   684.5  886.43   743.1  901.04   752.9  902.01   772.4  907.72   821.3  927.13
     831     929   850.6     937   870.1  941.82   899.4  955.24   909.2   957.9
#Mann= 3 , 0 , 0
       0     .06       0   421.9    .045       0   436.9     .06       0
Bank Sta=421.9,436.9
XS Rating Curve= 0 ,0
Exp/Cntr=0.3,0.1

Chan Stop Cuts=-1
Use User Specified Reach Order=0
Composite Channel Slope=5